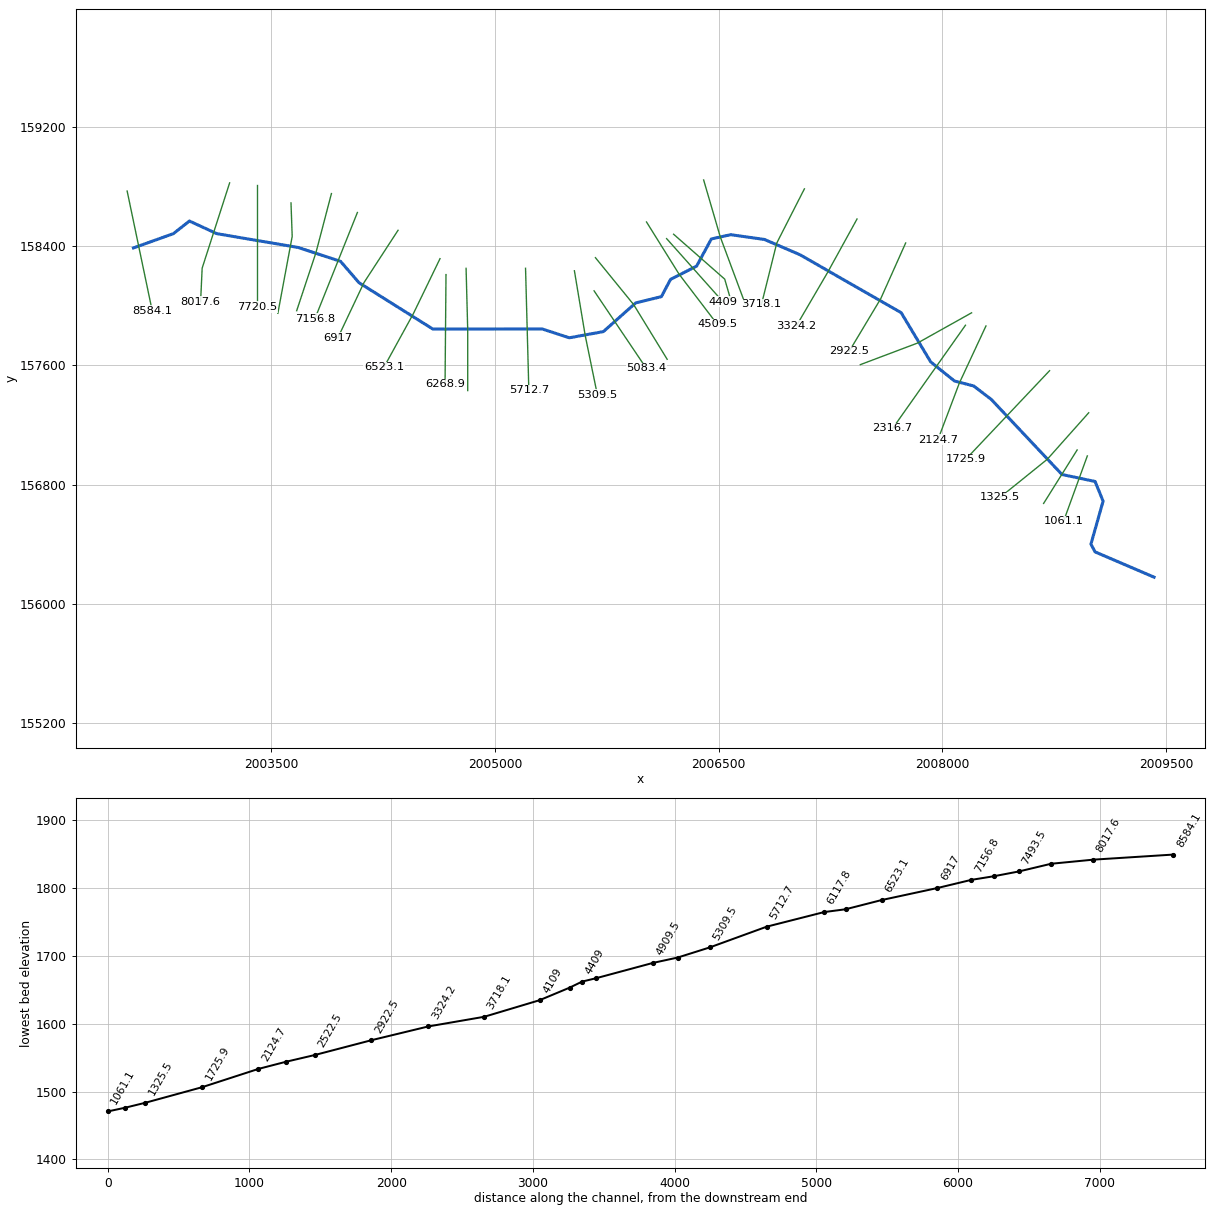
--- RndbtmCrk.prj (project) ---

Proj Title=RndbtmCrk
Current Plan=p01
Geom File=g01
Flow File=f01
Plan File=p01
DSS Export Rating Curves=0
DSS Export Rating Curve Sorted=0
DSS Export Volume Flow Curves=0
DXF OffsetX=0
DXF OffsetY=0
DXF ScaleX=0
DXF ScaleY=0

--- RndbtmCrk.p01 (plan) ---

Plan Title=Floodplain
Program Version=4.00
Geom File=g01
Flow File=f01
K Sum by GR=0
Std Step Tol=0.01
Critical Tol=0.01
Num of Std Step Trials=20
Max Error Tol=0.3
Flow Tol Ratio=0.001
Split Flow NTrial=30
Split Flow Tol=0.02
Split Flow Ratio=0.02
Log Output Level=0
Friction Slope Method=1
Unsteady Friction Slope Method=2
Unsteady Bridges Friction Slope Method=1
Global Log Level=0
CheckData=False
Run HTab=0
Run UNet=0
Run PostProcess=0
UNET Theta=0
UNET Theta Warmup=0
UNET ZTol=0
UNET ZSATol=0
UNET MxIter=0
UNET MaxInSteps=0
UNET DtIC=0
UNET DtMin=0
UNET MaxCRTS=0
UNET WFStab=0
UNET SFStab=0
UNET WFX=0
UNET SFX=0
UNET DSS MLevel=0
UNET DZMax Abort=0
UNET Convert EG Bridges=0
UNET Use Existing IB Tables=0
UNET Froude Limit=0
UNET Froude Power=0
Write IC File=0
Echo Input=False
Echo Output=False
Write Detailed=0

--- RndbtmCrk.f01 (steady flow) ---

Flow Title=NFF Regression Equation
Program Version=4.00
Number of Profiles=1
Profile Names=P100yr
River Rch & RM=RndbtmCrk,Main      ,8584.1
248.4440
River Rch & RM=RndbtmCrk,Main      ,7720.5
268.1283
River Rch & RM=RndbtmCrk,Main      ,7156.8
     297
River Rch & RM=RndbtmCrk,Main      ,5712.7
313.5187
River Rch & RM=RndbtmCrk,Main      ,5309.5
421.7177
River Rch & RM=RndbtmCrk,Main      ,4109
439.0425
River Rch & RM=RndbtmCrk,Main      ,3718.1
594.3168
River Rch & RM=RndbtmCrk,Main      ,3324.2
608.2601
River Rch & RM=RndbtmCrk,Main      ,1182.1
671.0274
Boundary for River Rch & Prof#=RndbtmCrk,Main      ,1
Up Type=0
Dn Type=3
Dn Slope=0.049236

--- RndbtmCrk.g01 (geometry) ---

Geom Title=USGS 3m DEM
Program Version=4.00

River Reach=RndbtmCrk     ,Main
Reach XY= 30
     2002576.149      158387.403     2002843.716      158483.062
     2002951.262      158567.679     2003134.852      158483.062
     2003680.609      158390.409     2003964.775      158297.252
     2004088.578      158154.098     2004583.789      157843.249
     2005316.983      157843.950     2005498.921      157784.680
     2005727.483      157826.173     2005944.497      158018.881
     2006116.372      158060.548     2006177.552      158176.208
     2006352.594      158265.403     2006451.442      158447.700
     2006581.343      158476.130     2006807.320      158444.244
     2007045.774      158341.653     2007724.402      157953.087
     2007922.319      157623.226     2008082.041      157494.754
     2008210.513      157461.768     2008328.569      157371.490
     2008802.527      156868.018     2009024.749      156821.143
     2009078.569      156689.198     2008996.971      156401.004
     2009024.749      156348.921     2009420.367      156179.388

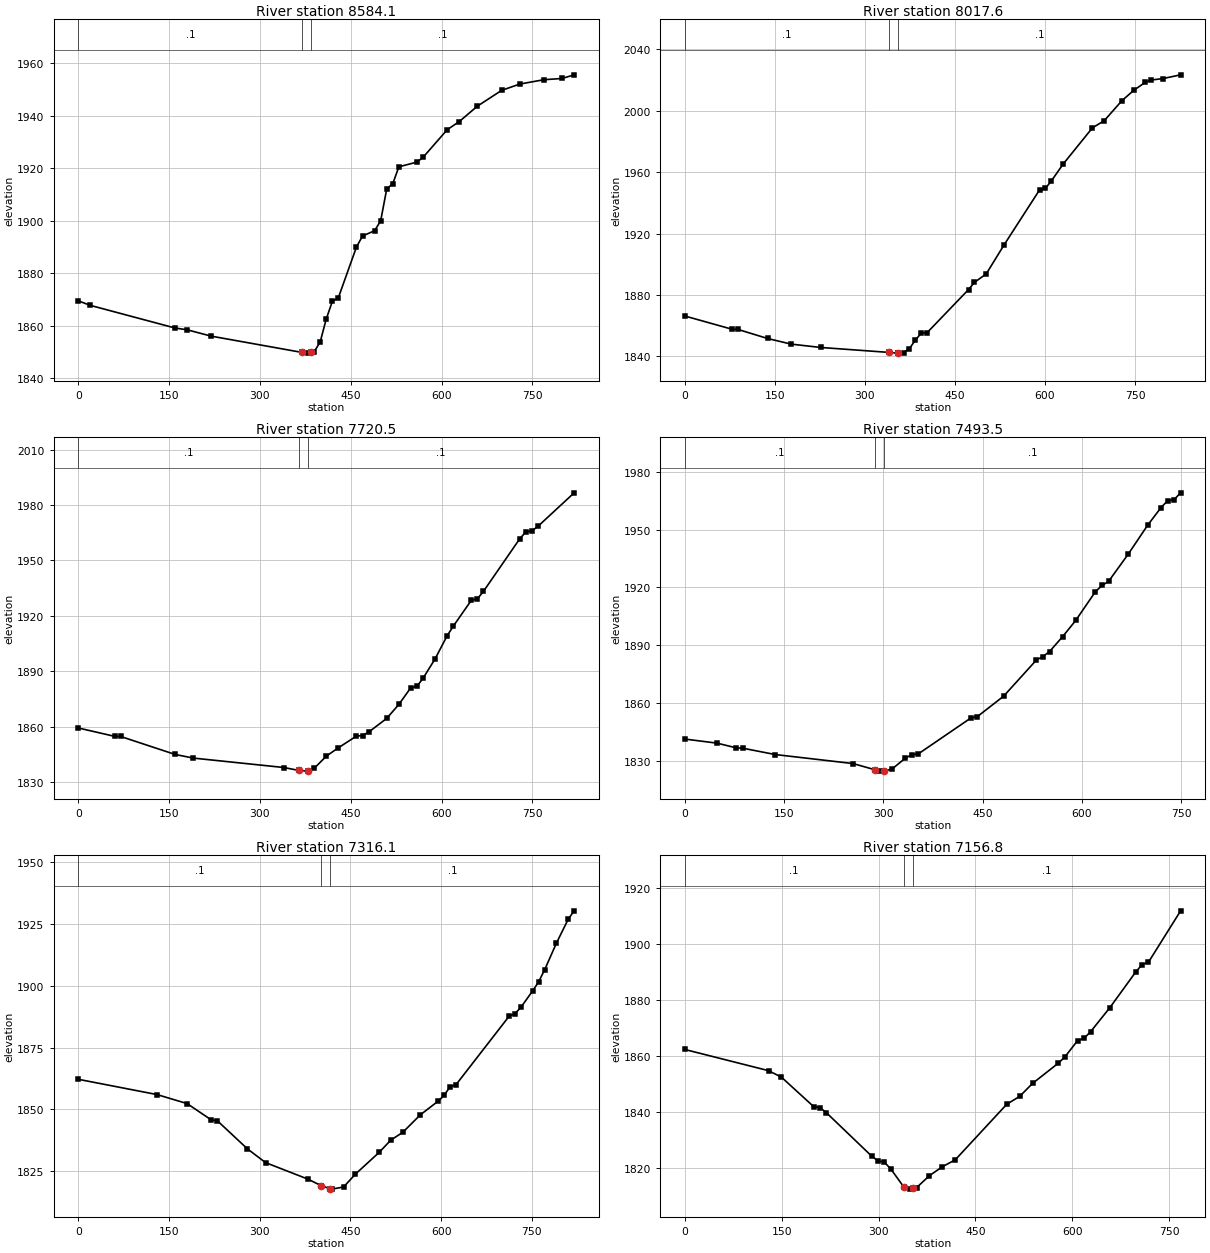
Type RM Length L Ch R = 1 ,8584.1,579,566.4,553.4
XS GIS Cut Line= 3
     2002533.588      158768.967     2002617.480      158368.152
     2002701.371      157967.337
#Sta/Elev= 30
       0 1869.51    20.0 1867.78   159.8 1859.17   179.8 1858.49   219.7 1856.07
   369.9 1849.86   379.5 1849.61   384.9 1849.88   389.5 1850.11   399.5 1853.86
   409.5 1862.60   419.5 1869.29   429.5 1870.70   459.4 1890.02   469.4 1894.19
   489.4 1896.24   499.4 1899.98   509.4 1912.13   519.4 1914.12   529.4 1920.56
   559.3 1922.36   569.3 1924.14   609.3 1934.69   629.2 1937.79   659.2 1943.67
   699.2 1949.67   729.1 1952.07   769.1 1953.73   799.0 1954.20   819.0 1955.59
#Mann= 3 , 0 , 0
       0     0.1       0   369.9   0.045       0   384.9     0.1       0
Bank Sta=   369.9,   384.9
Exp/Cntr=0.3,0.1

Type RM Length L Ch R = 1 ,8017.6,290,297.1,304.3
XS GIS Cut Line= 3
     2003220.857      158823.535     2003036.668      158251.749
     2003026.251      158026.737
#Sta/Elev= 30
       0 1866.27    78.8 1857.64    88.6 1857.52   137.9 1851.62   177.3 1847.94
   226.5 1845.77   340.8 1842.53   354.5 1842.08   355.8 1842.12   364.4 1842.42
   374.2 1845.05   384.1 1850.56   393.9 1855.09   403.8 1855.47   472.7 1883.52
   482.6 1888.22   502.2 1893.72   531.8 1912.56   590.9 1948.38   600.7 1949.45
   610.5 1954.20   630.1 1965.18   679.1 1988.90   698.7 1993.52   728.0 2006.50
   747.6 2013.24   767.2 2018.58   777.0 2020.04   796.6 2020.99   826.0 2023.43
#Mann= 3 , 0 , 0
       0     0.1       0   340.8   0.045       0   355.8     0.1       0
Bank Sta=   340.8,   355.8
Exp/Cntr=0.3,0.1

Type RM Length L Ch R = 1 ,7720.5,231.1,226.8,222.5
XS GIS Cut Line= 3
     2003405.360      158810.326     2003405.360      158400.826
     2003405.360      157991.326
#Sta/Elev= 30
       0 1859.38    59.9 1854.86    69.9 1854.79   159.8 1845.07   189.8 1843.10
   339.6 1837.99   364.4 1836.41   379.4 1836.04   389.5 1837.50   409.5 1844.12
   429.5 1848.66   459.4 1855.00   469.4 1855.28   479.4 1857.11   509.4 1864.58
   529.4 1872.10   549.3 1881.23   559.3 1881.93   569.3 1886.23   589.3 1896.76
   609.3 1909.34   619.2 1914.38   649.2 1928.48   659.2 1929.24   669.2 1933.30
   729.1 1961.73   739.1 1965.41   749.1 1966.00   759.1 1968.45   819.0 1986.60
#Mann= 3 , 0 , 0
       0     0.1       0   364.4   0.045       0   379.4     0.1       0
Bank Sta=   364.4,   379.4
Exp/Cntr=0.3,0.1

Type RM Length L Ch R = 1 ,7493.5,179,177.4,174.4
XS GIS Cut Line= 3
     2003632.479      158688.997     2003640.487      158464.767
     2003544.388      157949.038
#Sta/Elev= 30
       0 1841.36    48.8 1839.23    78.0 1836.76    87.8 1836.60   136.6 1833.32
   254.1 1828.65   286.6 1825.49   293.7 1824.74   301.6 1824.72   313.5 1825.94
   333.2 1831.46   343.2 1833.31   353.0 1833.73   432.2 1852.30   442.1 1853.04
   481.7 1863.63   531.2 1882.38   541.1 1884.17   551.0 1886.75   570.8 1894.51
   590.6 1902.92   620.3 1917.82   630.2 1921.03   640.1 1923.13   669.8 1937.26
   699.5 1952.44   719.3 1961.40   729.2 1964.94   739.1 1965.57   749.0 1969.09
#Mann= 3 , 0 , 0
       0     0.1       0   286.6   0.045       0   301.6     0.1       0
Bank Sta=   286.6,   301.6
Exp/Cntr=0.3,0.1

Type RM Length L Ch R = 1 ,7316.1,162,159.2,157.8
XS GIS Cut Line= 3
     2003903.593      158751.949     2003799.890      158355.986
     2003670.560      157966.358
#Sta/Elev= 30
       0 1862.12   129.8 1855.95   179.7 1852.30   219.6 1845.71   229.6 1845.38
   279.5 1833.96   309.5 1828.38   379.4 1821.70   401.8 1819.00   416.8 1817.75
   419.1 1817.63   438.6 1818.50   458.2 1823.72   497.3 1832.50   516.8 1837.52
   536.4 1840.63   565.7 1847.78   595.0 1853.28   604.8 1855.61   614.6 1859.10
   624.4 1859.92   712.3 1887.68   722.1 1888.74   731.9 1891.34   751.4 1898.02
   761.2 1901.68   771.0 1906.49   790.5 1917.30   810.1 1927.03   819.8 1930.37
#Mann= 3 , 0 , 0
       0     0.1       0   401.8   0.045       0   416.8     0.1       0
Bank Sta=   401.8,   416.8
Exp/Cntr=0.3,0.1

Type RM Length L Ch R = 1 ,7156.8,241.8,239.3,237.4
XS GIS Cut Line= 2
     2004077.735      158624.931     2003792.643      157912.201
#Sta/Elev= 30
       0 1862.29   129.6 1854.70   149.5 1852.39   199.4 1841.84   209.4 1841.47
   219.3 1839.61   289.1 1824.13   299.1 1822.39   309.0 1821.90   319.0 1819.46
   338.7 1813.14   348.9 1812.26   353.7 1812.53   358.9 1812.82   378.8 1817.10
   398.8 1820.29   418.7 1822.76   498.5 1842.68   518.4 1845.48   538.3 1850.12
   578.2 1857.38   588.2 1859.56   608.1 1865.46   618.1 1866.29   628.1 1868.62
   658.0 1877.26   697.8 1889.95   707.8 1892.69   717.8 1893.55   767.6 1911.96
#Mann= 3 , 0 , 0
       0     0.1       0   338.7   0.045       0   353.7     0.1       0
Bank Sta=   338.7,   353.7
Exp/Cntr=0.3,0.1

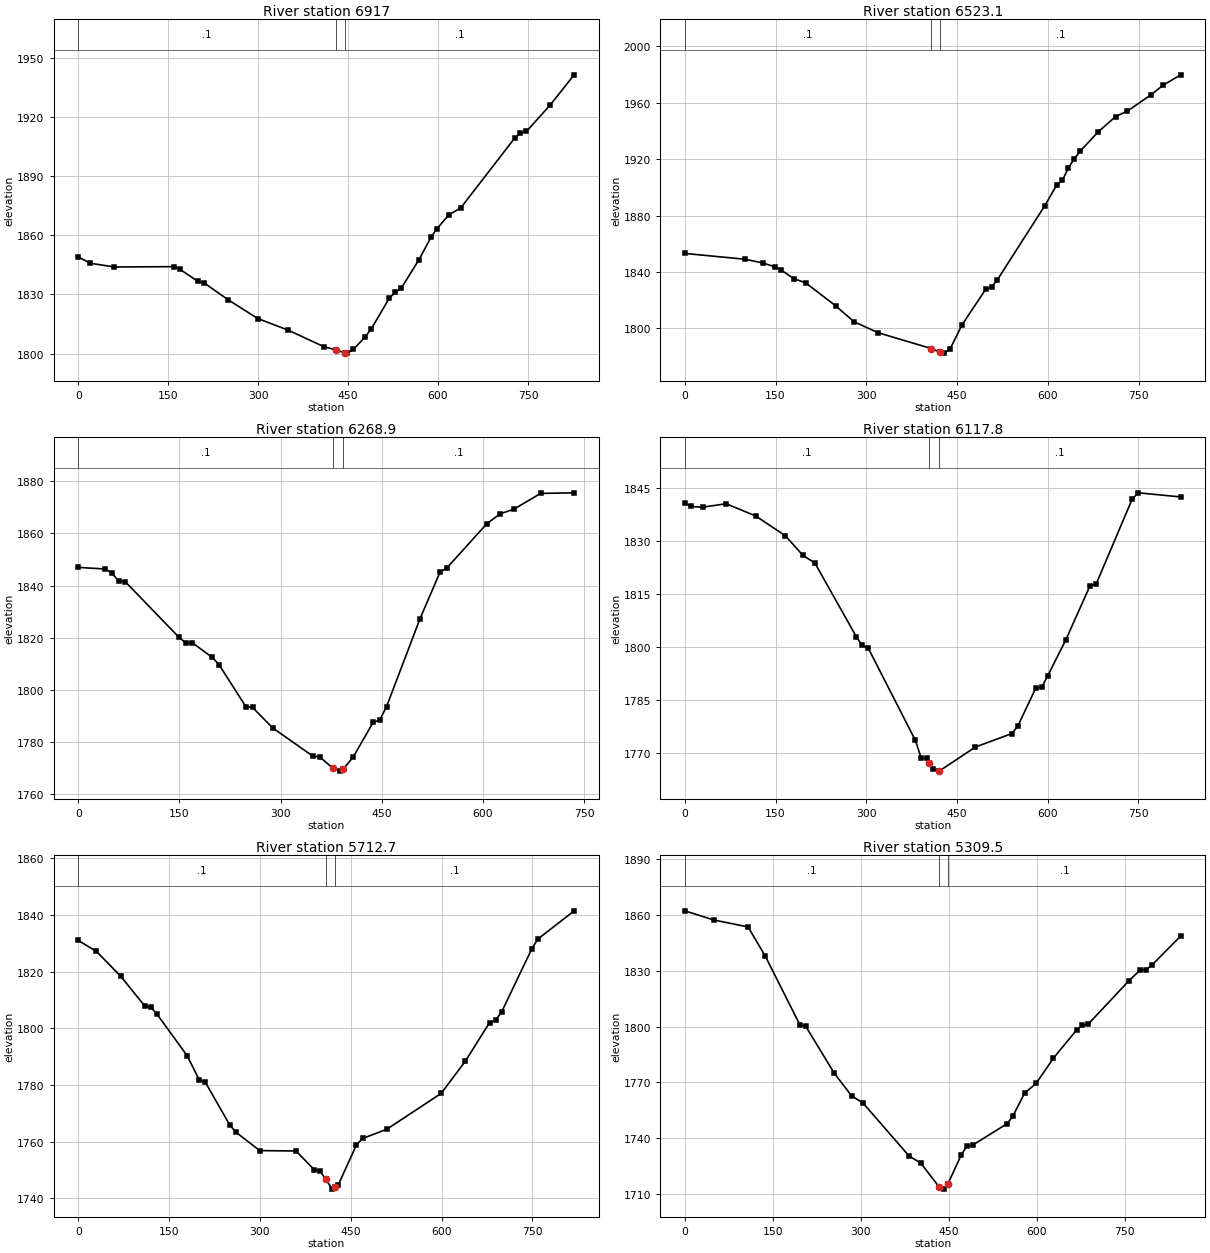
Type RM Length L Ch R = 1 ,6917,394,393.9,392.4
XS GIS Cut Line= 3
     2004350.404      158505.712     2004121.798      158154.558
     2003947.360      157785.775
#Sta/Elev= 30
       0 1848.96    20.0 1845.80    59.9 1843.89   159.6 1844.06   169.6 1842.67
   199.5 1836.60   209.5 1835.88   249.4 1827.38   299.3 1817.76   349.2 1811.98
   409.0 1803.58   429.8 1801.79   444.8 1800.35   448.9 1800.23   458.8 1802.11
   478.7 1808.58   488.7 1812.55   518.5 1828.00   528.5 1831.06   538.4 1833.06
   568.3 1847.66   588.2 1858.94   598.1 1863.23   618.0 1870.33   637.9 1873.86
   727.5 1909.11   737.4 1911.73   747.4 1912.58   787.2 1926.06   827.0 1941.29
#Mann= 3 , 0 , 0
       0     0.1       0   429.8   0.045       0   444.8     0.1       0
Bank Sta=   429.8,   444.8
Exp/Cntr=0.3,0.1

Type RM Length L Ch R = 1 ,6523.1,243.8,254.2,265.5
XS GIS Cut Line= 3
     2004631.670      158315.256     2004453.208      157946.818
     2004255.729      157587.334
#Sta/Elev= 30
       0 1853.17    99.8 1849.04   129.8 1846.35   149.8 1843.48   159.8 1841.29
   179.7 1835.39   199.7 1832.31   249.6 1815.94   279.6 1804.76   319.5 1796.94
   407.3 1785.73   422.3 1783.11   428.9 1782.47   438.7 1785.57   458.2 1802.54
   497.3 1827.69   507.0 1829.14   516.8 1834.60   594.9 1886.95   614.5 1901.56
   624.2 1905.15   634.0 1913.79   643.8 1920.28   653.5 1925.70   682.8 1939.18
   712.1 1950.27   731.6 1954.16   770.7 1965.70   790.2 1972.36   819.5 1979.83
#Mann= 3 , 0 , 0
       0     0.1       0   407.3   0.045       0   422.3     0.1       0
Bank Sta=   407.3,   422.3
Exp/Cntr=0.3,0.1

Type RM Length L Ch R = 1 ,6268.9,150.2,151,151.2
XS GIS Cut Line= 2
     2004671.945      158208.504     2004665.538      157473.351
#Sta/Elev= 30
       0 1846.97    39.7 1846.35    49.7 1844.86    59.6 1841.71    69.5 1841.51
   149.0 1820.24   159.0 1818.12   168.9 1818.11   198.7 1812.46   208.6 1809.70
   248.4 1793.59   258.3 1793.33   288.1 1785.47   347.7 1774.65   357.7 1774.40
   377.7 1769.98   387.5 1768.90   392.7 1769.67   407.3 1774.19   437.1 1787.55
   447.1 1788.56   457.0 1793.60   506.7 1827.36   536.5 1845.25   546.4 1846.74
   606.0 1863.78   625.9 1867.54   645.8 1869.27   685.5 1875.32   735.2 1875.54
#Mann= 3 , 0 , 0
       0     0.1       0   377.7   0.045       0   392.7     0.1       0
Bank Sta=   377.7,   392.7
Exp/Cntr=0.3,0.1

Type RM Length L Ch R = 1 ,6117.8,405,405.1,405.7
XS GIS Cut Line= 3
     2004806.602      158250.516     2004817.531      157840.062
     2004817.531      157430.756
#Sta/Elev= 30
       0 1840.89     9.8 1839.84    29.3 1839.62    68.4 1840.62   117.3 1837.14
   166.2 1831.55   195.5 1825.94   215.1 1823.80   283.5 1802.94   293.3 1800.41
   303.1 1799.73   381.3 1773.50   391.0 1768.43   400.8 1768.39   404.6 1767.19
   410.6 1765.29   419.6 1764.82   420.6 1764.77   480.5 1771.60   540.4 1775.40
   550.4 1777.44   580.3 1788.29   590.3 1788.60   600.3 1791.87   630.2 1802.06
   670.2 1817.40   680.1 1817.79   740.0 1842.01   750.0 1843.71   819.9 1842.55
#Mann= 3 , 0 , 0
       0     0.1       0   404.6   0.045       0   419.6     0.1       0
Bank Sta=   404.6,   419.6
Exp/Cntr=0.3,0.1

Type RM Length L Ch R = 1 ,5712.7,399.9,403.1,407.1
XS GIS Cut Line= 3
     2005205.370      158250.850     2005216.434      157841.499
     2005227.498      157432.149
#Sta/Elev= 30
       0 1830.95    30.0 1827.08    69.9 1818.35   109.9 1807.79   119.8 1807.38
   129.8 1805.00   179.8 1790.30   199.8 1781.72   209.7 1780.98   249.7 1766.02
   259.7 1763.43   299.6 1756.84   359.6 1756.70   389.5 1750.14   399.5 1749.55
   408.8 1746.65   419.5 1743.25   423.8 1743.92   429.5 1744.81   459.4 1758.87
   469.4 1761.11   509.4 1764.35   599.3 1777.01   639.2 1788.34   679.2 1801.96
   689.2 1802.84   699.2 1805.74   749.1 1828.02   759.1 1831.44   819.0 1841.40
#Mann= 3 , 0 , 0
       0     0.1       0   408.8   0.045       0   423.8     0.1       0
Bank Sta=   408.8,   423.8
Exp/Cntr=0.3,0.1

Type RM Length L Ch R = 1 ,5309.5,216.4,226.1,234.9
XS GIS Cut Line= 3
     2005533.049      158234.134     2005605.682      157798.962
     2005686.844      157403.293
#Sta/Elev= 30
       0 1862.29    49.0 1857.40   107.8 1853.62   137.3 1837.86   196.1 1800.99
   205.9 1800.28   254.9 1774.85   284.3 1762.78   303.9 1758.85   382.4 1730.34
   402.0 1726.64   433.7 1713.68   441.2 1712.57   448.7 1715.55   470.8 1730.72
   480.6 1735.73   490.4 1736.20   549.6 1747.81   559.4 1751.93   579.1 1764.21
   598.8 1769.44   628.4 1783.08   667.8 1798.17   677.6 1800.78   687.5 1801.30
   756.4 1824.49   776.1 1830.39   786.0 1830.54   795.8 1832.97   845.1 1848.70
#Mann= 3 , 0 , 0
       0     0.1       0   433.7   0.045       0   448.7     0.1       0
Bank Sta=   433.7,   448.7
Exp/Cntr=0.3,0.1

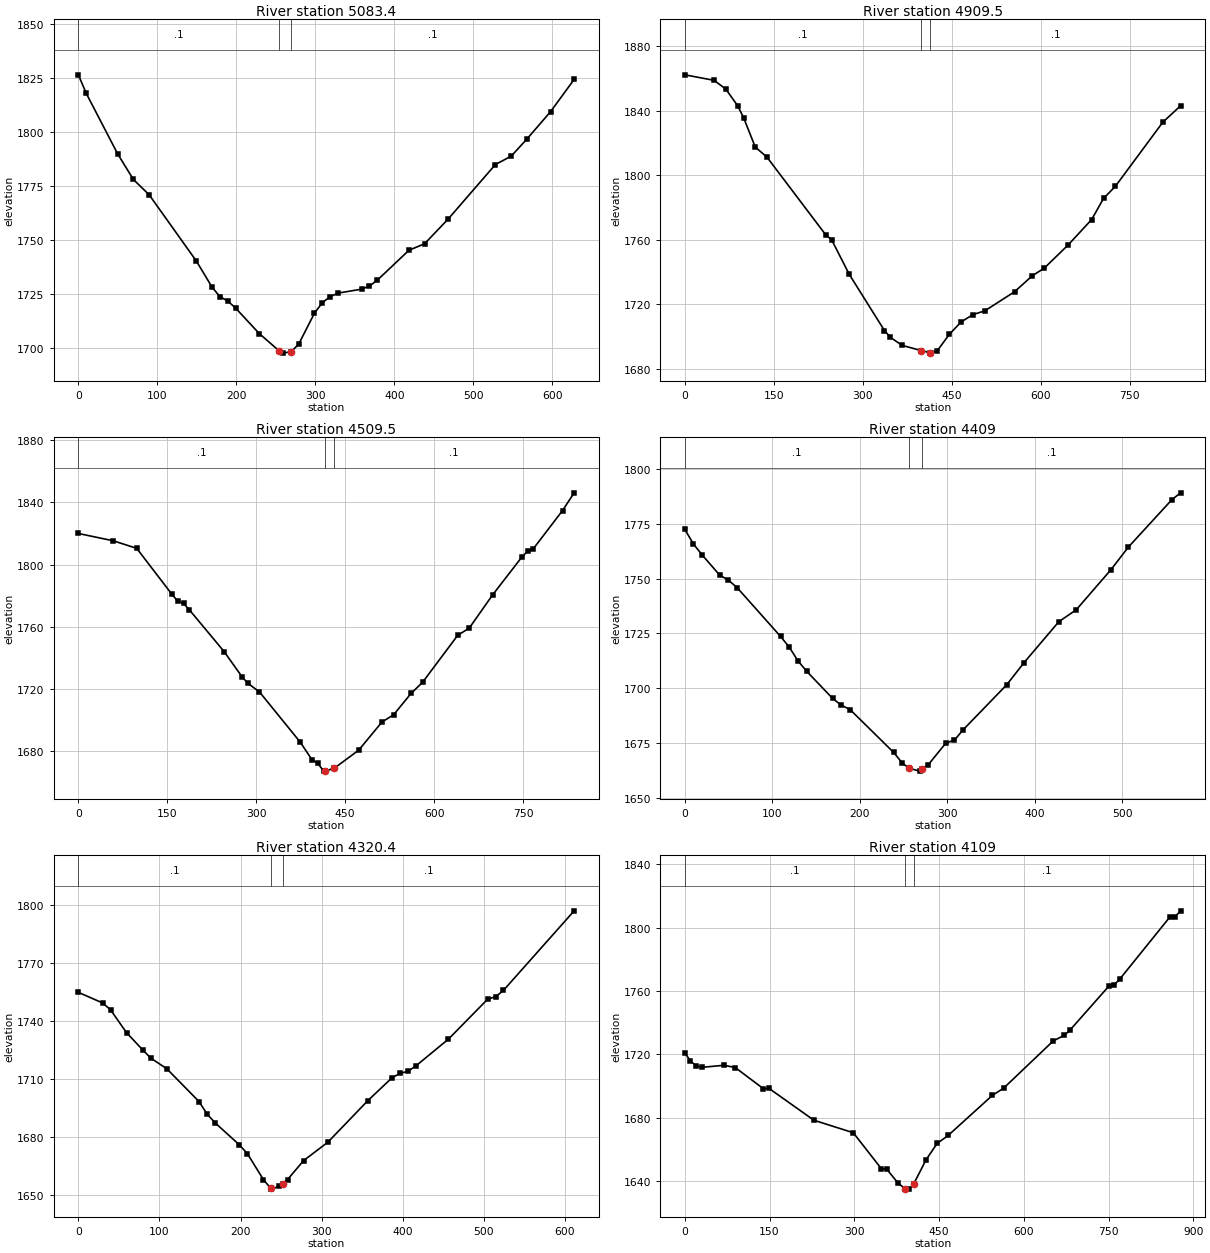
Type RM Length L Ch R = 1 ,5083.4,171.9,173.9,172.9
XS GIS Cut Line= 2
     2005664.963      158099.593     2006015.722      157579.059
#Sta/Elev= 30
       0 1826.31    10.0 1817.76    49.8 1789.75    69.7 1777.93    89.7 1770.84
   149.4 1740.24   169.4 1728.10   179.3 1723.73   189.3 1721.73   199.3 1718.40
   229.2 1706.65   254.4 1698.66   259.0 1697.66   269.4 1698.30   279.0 1701.83
   298.9 1716.12   308.9 1720.99   318.8 1723.76   328.8 1725.40   358.7 1727.24
   368.6 1728.69   378.6 1731.41   418.5 1745.20   438.4 1748.24   468.3 1759.68
   528.0 1784.85   548.0 1788.71   567.9 1796.63   597.8 1809.28   627.7 1824.20
#Mann= 3 , 0 , 0
       0     0.1       0   254.4   0.045       0   269.4     0.1       0
Bank Sta=   254.4,   269.4
Exp/Cntr=0.3,0.1

Type RM Length L Ch R = 1 ,4909.5,401.1,399.6,402.5
XS GIS Cut Line= 3
     2005673.968      158322.011     2005930.353      158007.356
     2006154.984      157640.698
#Sta/Elev= 30
       0 1862.13    49.5 1858.72    69.3 1853.22    89.1 1842.97    99.0 1835.70
   118.8 1817.39   138.6 1811.12   237.6 1763.03   247.5 1760.02   277.2 1738.59
   336.6 1703.76   346.5 1699.59   366.3 1694.58   398.4 1691.39   413.4 1690.04
   415.9 1689.78   425.9 1691.35   445.9 1701.40   465.9 1709.12   485.9 1713.65
   505.9 1715.99   555.9 1727.78   585.9 1737.72   605.9 1742.36   645.9 1756.64
   685.9 1772.50   705.9 1785.57   725.9 1793.08   805.9 1832.79   835.9 1842.98
#Mann= 3 , 0 , 0
       0     0.1       0   398.4   0.045       0   413.4     0.1       0
Bank Sta=   398.4,   413.4
Exp/Cntr=0.3,0.1

Type RM Length L Ch R = 1 ,4509.5,97.6,100.8,102.6
XS GIS Cut Line= 3
     2006016.570      158561.336     2006235.729      158210.287
     2006491.892      157874.427
#Sta/Elev= 30
       0 1819.97    59.1 1815.25    98.5 1810.40   157.6 1781.00   167.5 1776.53
   177.4 1775.01   187.2 1770.94   246.3 1743.88   275.9 1727.99   285.8 1723.75
   305.5 1718.17   374.4 1685.82   394.1 1674.59   404.0 1672.22   413.8 1667.29
   416.7 1667.31   431.7 1669.17   472.8 1680.74   512.1 1698.85   531.7 1703.48
   561.2 1717.22   580.8 1724.46   639.8 1754.53   659.4 1759.23   698.7 1780.53
   747.8 1804.73   757.7 1808.60   767.5 1810.22   816.6 1834.71   836.2 1846.08
#Mann= 3 , 0 , 0
       0     0.1       0   416.7   0.045       0   431.7     0.1       0
Bank Sta=   416.7,   431.7
Exp/Cntr=0.3,0.1

Type RM Length L Ch R = 1 ,4409,85.6,88.6,91.5
XS GIS Cut Line= 2
     2006151.374      158449.882     2006528.600      158026.931
#Sta/Elev= 30
       0 1772.44     9.9 1765.72    19.9 1760.73    39.8 1751.59    49.7 1749.31
    59.7 1745.89   109.4 1723.62   119.3 1718.77   129.3 1712.49   139.2 1707.75
   169.0 1695.31   179.0 1692.21   188.9 1690.26   238.6 1670.74   248.6 1665.86
   256.3 1663.50   268.4 1662.18   271.3 1663.04   278.4 1665.16   298.3 1674.94
   308.2 1676.33   318.2 1681.06   367.9 1701.54   387.8 1711.68   427.5 1730.32
   447.4 1735.75   487.2 1754.10   507.1 1764.39   556.8 1786.00   566.7 1789.08
#Mann= 3 , 0 , 0
       0     0.1       0   256.3   0.045       0   271.3     0.1       0
Bank Sta=   256.3,   271.3
Exp/Cntr=0.3,0.1

Type RM Length L Ch R = 1 ,4320.4,224.9,211.3,199.3
XS GIS Cut Line= 3
     2006198.310      158479.182     2006541.061      158178.073
     2006584.306      158029.121
#Sta/Elev= 30
       0 1754.86    29.8 1749.40    39.7 1745.84    59.5 1733.98    79.3 1725.17
    89.3 1720.88   109.1 1715.38   148.8 1698.44   158.7 1691.99   168.6 1687.46
   198.4 1676.14   208.3 1671.61   228.1 1658.18     237 1653.71   238.0 1653.21
   248.0 1654.72     252 1656.10   257.9 1658.14   277.7 1667.94   307.5 1677.39
   357.0 1698.94   386.8 1710.76   396.7 1712.99   406.6 1714.11   416.6 1717.01
   456.2 1730.65   504.7 1751.34   514.4 1752.57   524.1 1755.86   611.3 1796.96
#Mann= 3 , 0 , 0
       0     0.1       0     237   0.045       0     252     0.1       0
Bank Sta=     237,     252
Exp/Cntr=0.3,0.1

Type RM Length L Ch R = 1 ,4109,404.2,390.9,377.3
XS GIS Cut Line= 3
     2006399.774      158842.976     2006511.243      158461.358
     2006678.768      158011.496
#Sta/Elev= 30
       0 1720.97     9.9 1715.74    19.9 1712.75    29.8 1711.72    69.6 1713.04
    89.4 1711.57   139.2 1698.21   149.1 1698.40   228.6 1678.28   298.2 1670.40
   347.9 1647.66   357.8 1647.18   377.7 1638.46   390.1 1634.98   397.6 1634.75
   405.1 1638.02   427.0 1653.28   446.6 1663.61   466.1 1668.66   544.5 1694.04
   564.1 1698.49   652.3 1728.48   671.9 1731.99   681.7 1735.23   750.2 1762.90
   760.0 1763.87   769.8 1767.46   858.0 1806.50   867.8 1806.96   877.6 1810.66
#Mann= 3 , 0 , 0
       0     0.1       0   390.1   0.045       0   405.1     0.1       0
Bank Sta=   390.1,   405.1
Exp/Cntr=0.3,0.1

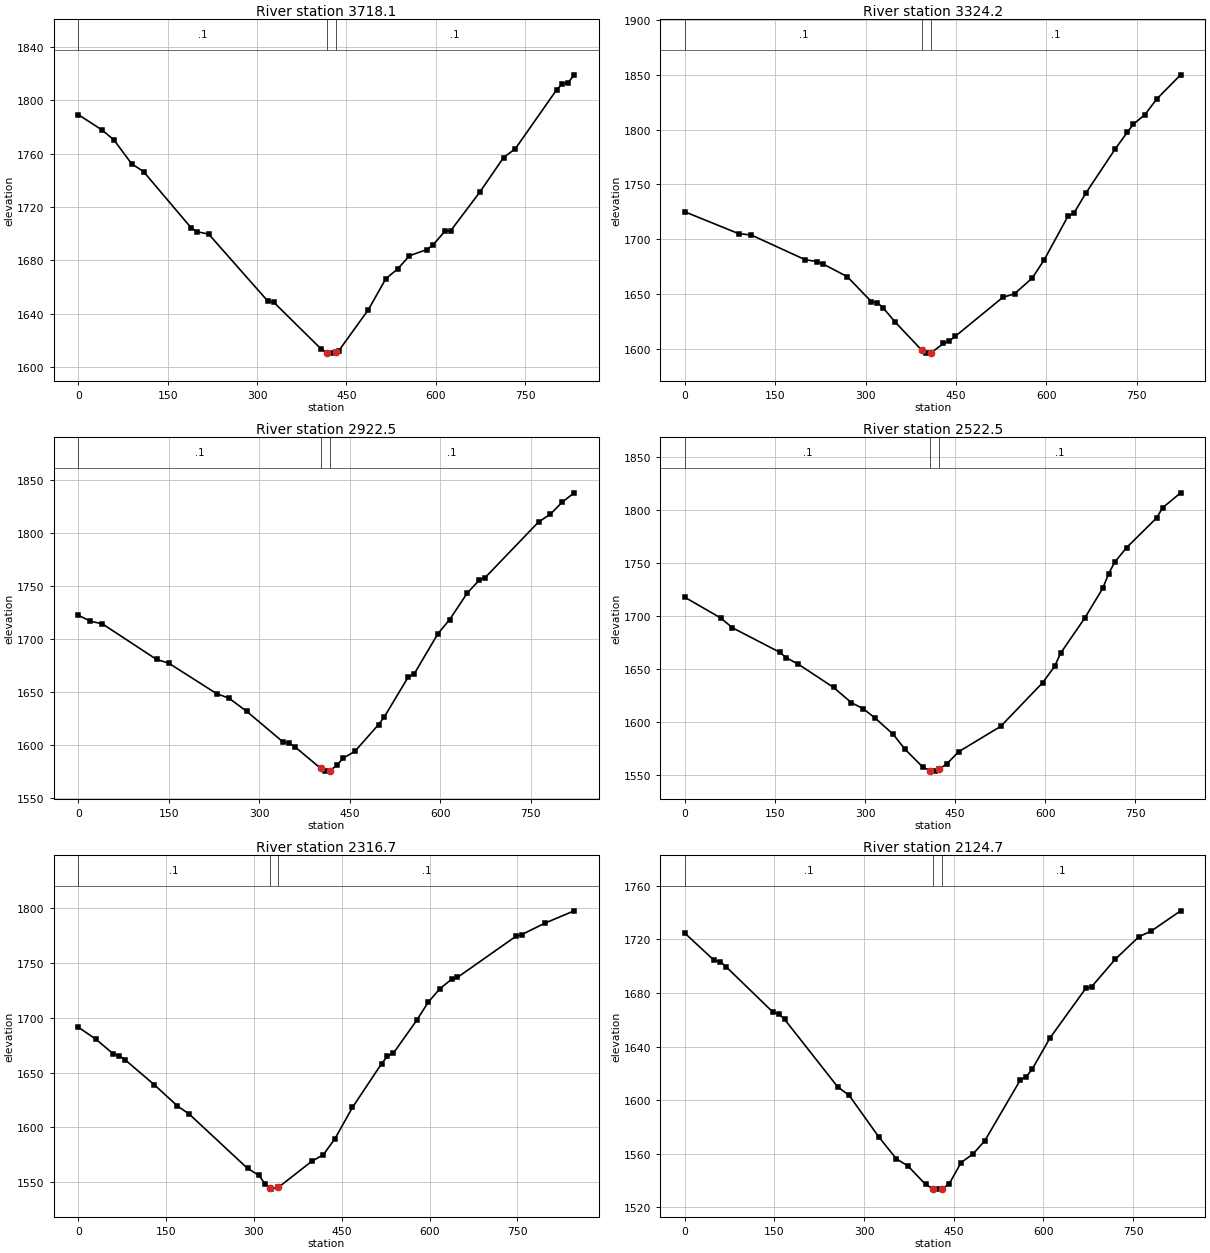
Type RM Length L Ch R = 1 ,3718.1,398.3,393.8,387.6
XS GIS Cut Line= 3
     2007075.353      158783.519     2006890.121      158420.299
     2006787.503      158008.321
#Sta/Elev= 30
       0 1789.24    39.8 1777.74    59.7 1770.30    89.5 1752.37   109.4 1746.54
   189.0 1704.51   198.9 1701.43   218.8 1699.61   318.2 1649.24   328.2 1648.39
   407.7 1613.34   417.2 1610.55   427.5 1610.29   432.2 1611.19   437.4 1612.19
   486.7 1642.77   516.3 1666.21   536.1 1673.47   555.8 1683.36   585.4 1688.04
   595.3 1691.47   615.1 1701.59   624.9 1702.06   674.3 1731.33   713.8 1757.06
   733.6 1763.70   802.7 1807.76   812.5 1812.41   822.4 1813.36   832.3 1819.13
#Mann= 3 , 0 , 0
       0     0.1       0   417.2   0.045       0   432.2     0.1       0
Bank Sta=   417.2,   432.2
Exp/Cntr=0.3,0.1

Type RM Length L Ch R = 1 ,3324.2,400,401.7,401.2
XS GIS Cut Line= 3
     2007428.334      158581.287     2007230.851      158222.680
     2007022.311      157865.860
#Sta/Elev= 30
       0 1725.07    89.9 1705.01   109.8 1704.02   199.7 1681.33   219.7 1679.64
   229.7 1677.32   269.6 1665.86   309.5 1643.10   319.5 1642.13   329.5 1637.13
   349.5 1624.16   393.2 1598.69   399.4 1596.07   408.2 1596.12   429.1 1604.91
   438.9 1607.25   448.8 1611.42   527.5 1646.90   547.2 1650.28   576.7 1664.70
   596.4 1681.32   635.7 1720.95   645.6 1723.77   665.2 1741.92   714.4 1782.61
   734.1 1797.56   744.0 1804.87   763.6 1813.87   783.3 1828.12   822.7 1850.09
#Mann= 3 , 0 , 0
       0     0.1       0   393.2   0.045       0   408.2     0.1       0
Bank Sta=   393.2,   408.2
Exp/Cntr=0.3,0.1

Type RM Length L Ch R = 1 ,2922.5,414.6,400,384.8
XS GIS Cut Line= 3
     2007754.460      158420.491     2007587.460      158047.200
     2007375.444      157693.184
#Sta/Elev= 30
       0 1722.65    20.0 1717.10    39.9 1714.57   129.7 1681.01   149.6 1677.59
   229.4 1648.71   249.4 1644.60   279.3 1631.98   339.1 1603.28   349.1 1602.05
   359.1 1598.57   401.4 1578.46   408.9 1575.76   416.4 1576.09   428.6 1581.20
   438.4 1587.87   458.1 1594.29   497.4 1619.63   507.2 1627.04   546.5 1664.35
   556.3 1667.15   595.6 1705.11   615.3 1718.64   644.7 1743.84   664.4 1755.76
   674.2 1758.27   762.6 1810.62   782.3 1818.01   801.9 1829.34   821.6 1838.11
#Mann= 3 , 0 , 0
       0     0.1       0   401.4   0.045       0   416.4     0.1       0
Bank Sta=   401.4,   416.4
Exp/Cntr=0.3,0.1

Type RM Length L Ch R = 1 ,2522.5,195.5,205.8,219.3
XS GIS Cut Line= 3
     2008196.625      157952.247     2007833.378      157749.090
     2007450.479      157604.596
#Sta/Elev= 30
       0 1717.90    59.5 1698.47    79.3 1689.12   158.6 1665.87   168.5 1660.95
   188.3 1655.02   247.7 1632.84   277.5 1618.42   297.3 1612.67   317.1 1603.84
   346.8 1588.74   366.6 1574.56   396.4 1557.66   408.7 1554.14   416.2 1553.90
   423.7 1555.83   436.2 1560.75   456.1 1572.25   526.0 1596.16   595.9 1637.39
   615.8 1652.80   625.8 1665.24   665.8 1698.22   695.7 1726.18   705.7 1740.07
   715.6 1750.92   735.6 1764.79   785.5 1792.73   795.5 1802.30   825.5 1816.41
#Mann= 3 , 0 , 0
       0     0.1       0   408.7   0.045       0   423.7     0.1       0
Bank Sta=   408.7,   423.7
Exp/Cntr=0.3,0.1

Type RM Length L Ch R = 1 ,2316.7,188,192,197.8
XS GIS Cut Line= 2
     2008155.517      157868.956     2007667.016      157177.047
#Sta/Elev= 30
       0 1691.41    29.9 1680.46    59.8 1667.06    69.8 1665.43    79.7 1661.77
   129.5 1639.06   169.4 1619.55   189.3 1612.28   289.0 1562.73   308.9 1556.31
   318.9 1548.32   326.7 1544.77   328.8 1543.82   341.7 1545.42   398.6 1569.12
   418.5 1575.17   438.4 1589.78   468.3 1618.27   518.2 1658.30   528.1 1664.99
   538.1 1667.62   577.9 1697.58   597.9 1714.33   617.8 1726.56   637.7 1735.12
   647.7 1736.80   747.3 1774.17   757.3 1775.78   797.2 1786.24   847.0 1797.45
#Mann= 3 , 0 , 0
       0     0.1       0   326.7   0.045       0   341.7     0.1       0
Bank Sta=   326.7,   341.7
Exp/Cntr=0.3,0.1

Type RM Length L Ch R = 1 ,2124.7,406.2,398.7,389.4
XS GIS Cut Line= 3
     2008292.932      157864.051     2008114.526      157481.076
     2007970.429      157100.443
#Sta/Elev= 30
       0 1724.73    49.1 1704.40    59.0 1703.51    68.8 1699.74   147.4 1665.69
   157.2 1664.34   167.0 1660.28   255.5 1609.98   275.1 1603.41   324.2 1572.63
   353.7 1556.14   373.4 1550.68   402.8 1536.90     415 1533.84   422.5 1533.40
     430 1533.51   442.3 1537.32   462.2 1553.26   482.0 1559.60   501.9 1569.54
   561.5 1615.13   571.4 1617.41   581.3 1623.19   611.1 1646.48   670.7 1683.39
   680.6 1684.67   720.3 1705.31   760.0 1722.17   779.8 1726.12   829.5 1741.41
#Mann= 3 , 0 , 0
       0     0.1       0     415   0.045       0     430     0.1       0
Bank Sta=     415,     430
Exp/Cntr=0.3,0.1

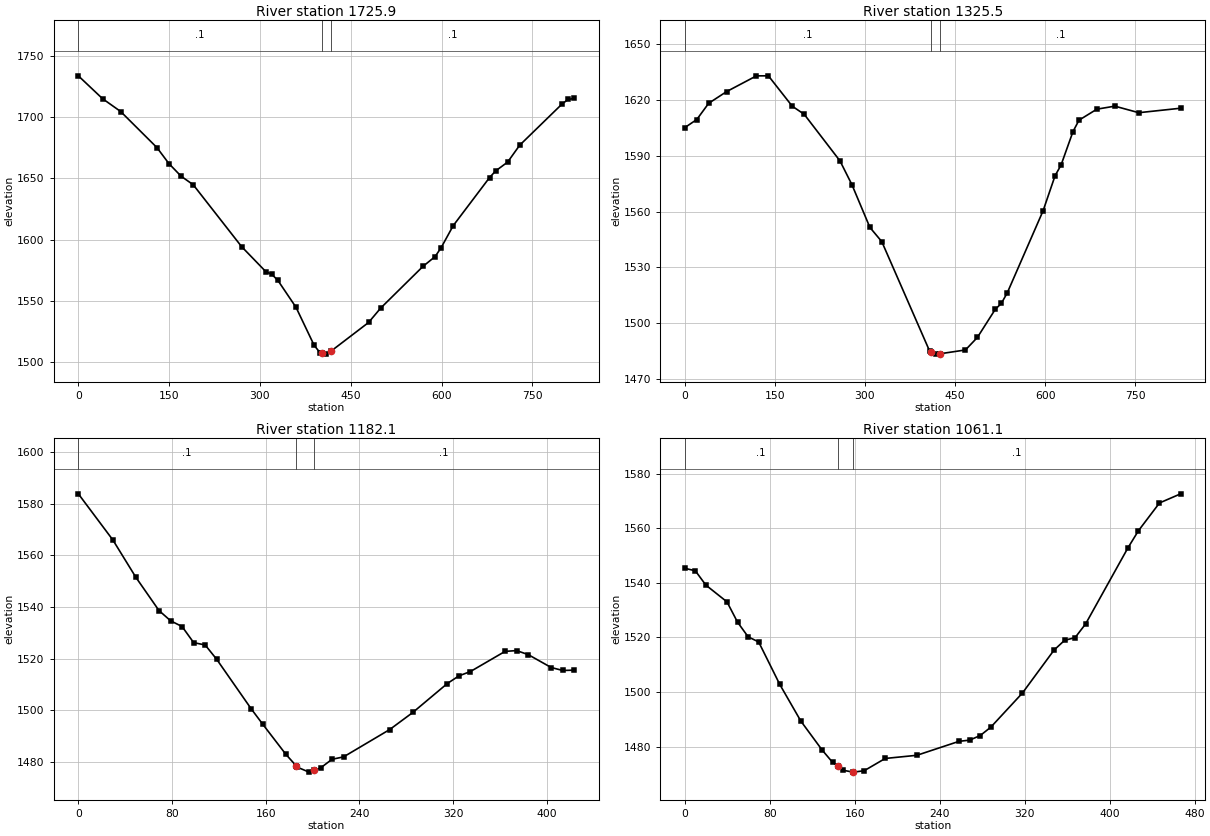
Type RM Length L Ch R = 1 ,1725.9,399.6,400.3,397.3
XS GIS Cut Line= 3
     2008719.628      157564.129     2008438.219      157266.640
     2008156.811      156969.152
#Sta/Elev= 30
       0 1733.82    40.0 1715.14    69.9 1704.66   129.8 1675.18   149.8 1661.98
   169.8 1651.76   189.8 1644.78   269.7 1594.22   309.6 1573.82   319.6 1571.61
   329.6 1566.61   359.6 1544.59   389.5 1513.57   399.5 1507.36     402 1507.11
   409.5 1506.36     417 1508.65   479.4 1532.22   499.4 1543.98   569.3 1578.08
   589.3 1586.07   599.3 1593.38   619.2 1611.35   679.2 1650.64   689.2 1656.05
   709.1 1663.32   729.1 1677.15   799.0 1710.78   809.0 1714.53   819.0 1715.31
#Mann= 3 , 0 , 0
       0     0.1       0     402   0.045       0     417     0.1       0
Bank Sta=     402,     417
Exp/Cntr=0.3,0.1

Type RM Length L Ch R = 1 ,1325.5,139.6,143.4,151.2
XS GIS Cut Line= 3
     2008982.065      157281.954     2008704.398      156970.183
     2008386.736      156714.004
#Sta/Elev= 30
       0 1605.17    19.9 1609.50    39.8 1618.25    69.6 1624.52   119.3 1632.99
   139.2 1633.00   178.9 1616.68   198.8 1612.33   258.4 1587.28   278.3 1574.48
   308.2 1551.53   328.0 1543.89   407.6 1485.10     410 1484.69   417.5 1483.42
     425 1483.62   467.3 1485.66   487.2 1492.40   517.0 1507.51   527.0 1510.66
   536.9 1516.32   596.6 1560.48   616.6 1579.36   626.5 1585.04   646.4 1603.06
   656.4 1609.17   686.2 1615.09   716.1 1616.70   755.9 1613.18   825.6 1615.59
#Mann= 3 , 0 , 0
       0     0.1       0     410   0.045       0     425     0.1       0
Bank Sta=     410,     425
Exp/Cntr=0.3,0.1

Type RM Length L Ch R = 1 ,1182.1,115.9,121.1,126.1
XS GIS Cut Line= 2
     2008904.551      157032.632     2008679.610      156673.864
#Sta/Elev= 30
       0 1583.77    29.5 1565.91    49.2 1551.42    68.9 1538.59    78.8 1534.64
    88.6 1532.41    98.5 1526.18   108.3 1525.29   118.2 1519.70   147.7 1500.52
   157.6 1494.54   177.3 1482.92     186 1478.53   187.1 1477.98   197.0 1476.08
     201 1476.73   206.8 1477.68   216.6 1481.04   226.5 1481.98   265.9 1492.56
   285.6 1499.16   315.1 1510.37   325.0 1513.33   334.8 1515.00   364.4 1522.80
   374.2 1523.11   384.1 1521.57   403.8 1516.56   413.6 1515.42   423.4 1515.54
#Mann= 3 , 0 , 0
       0     0.1       0     186   0.045       0     201     0.1       0
Bank Sta=     186,     201
Exp/Cntr=0.3,0.1

Type RM Length L Ch R = 1 ,1061.1,1062.9,1060.8,1058.8
XS GIS Cut Line= 2
     2008972.888      156992.769     2008813.436      156554.275
#Sta/Elev= 30
       0 1545.35     9.9 1544.44    19.8 1539.20    39.7 1533.05    49.6 1525.63
    59.6 1520.24    69.5 1518.36    89.4 1502.77   109.2 1489.36   129.1 1478.82
   139.0 1474.26   143.7 1472.87   148.9 1471.33   158.7 1470.65   168.8 1471.16
   188.6 1475.66   218.4 1476.82   258.1 1481.94   268.0 1482.37   278.0 1484.06
   287.9 1487.10   317.7 1499.62   347.5 1515.39   357.4 1518.95   367.3 1519.95
   377.2 1524.97   417.0 1552.83   426.9 1559.12   446.7 1569.29   466.6 1572.64
#Mann= 3 , 0 , 0
       0     0.1       0   143.7   0.045       0   158.7     0.1       0
Bank Sta=   143.7,   158.7
Exp/Cntr=0.3,0.1